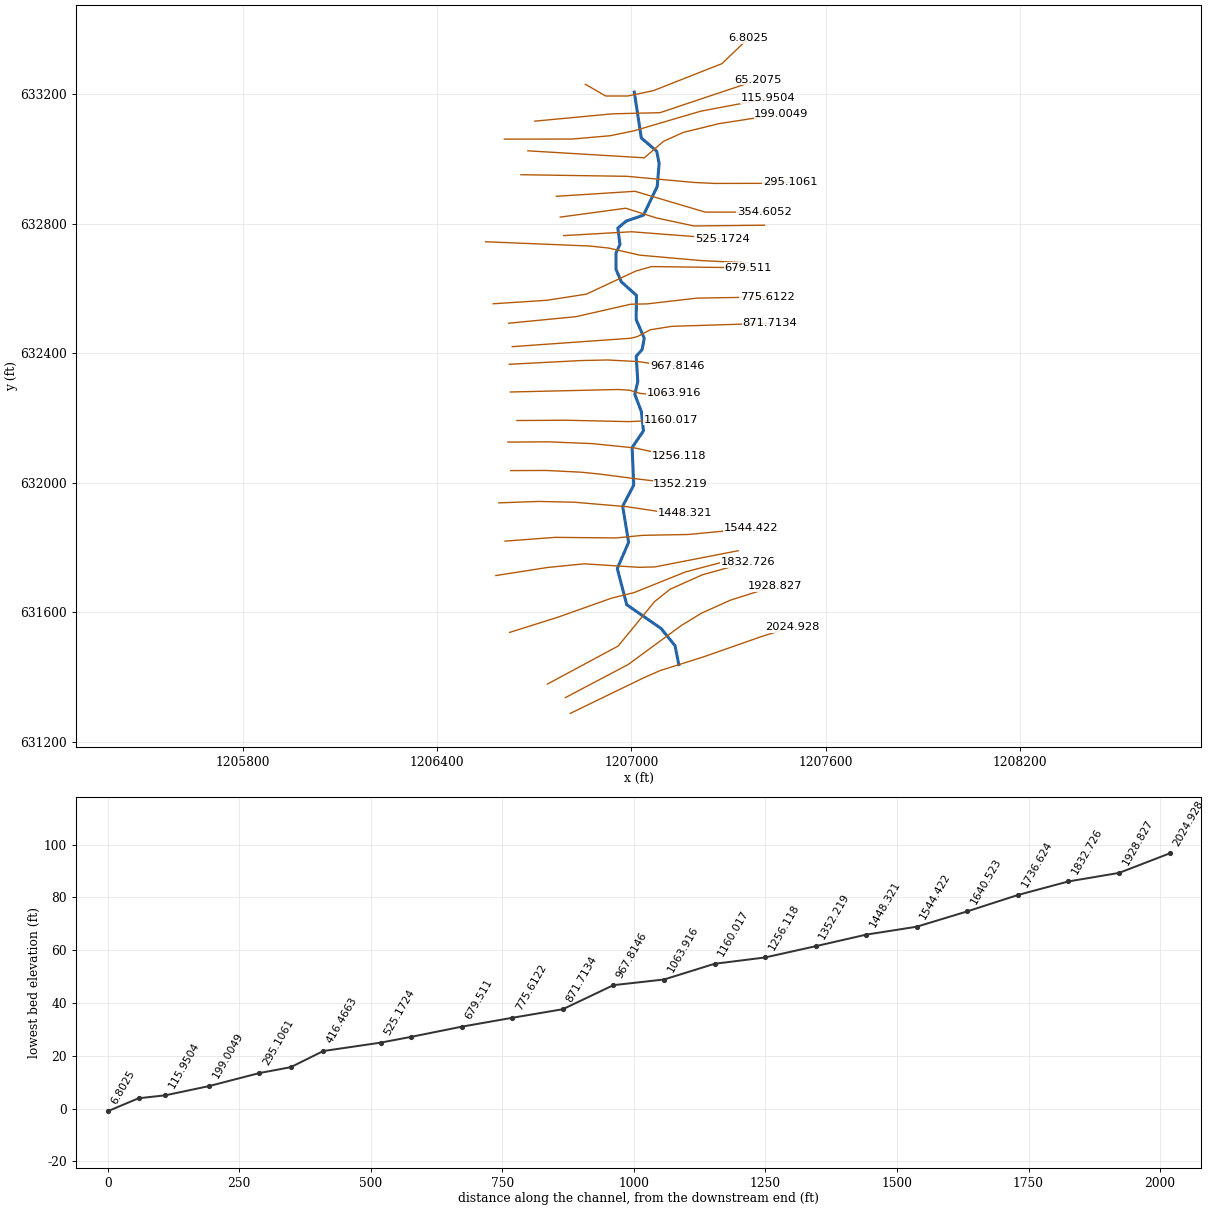
--- 506_ras.prj (project) ---

Proj Title=506
Current Plan=p01
Default Exp/Contr=0.3,0.1
English Units
Geom File=g01
Flow File=f01
Plan File=p01
Y Axis Title=Elevation
X Axis Title(PF)=Main Channel Distance
X Axis Title(XS)=Station
BEGIN DESCRIPTION:
RFD model 506 exported to HEC-RAS
END DESCRIPTION:

--- 506_ras.p01 (plan) ---

Plan Title=Plan 01
Program Version=4.10
Short Identifier=Plan 01
Geom File=g01
Flow File=f01
Subcritical Flow
Calc Critical at every XS
Secant Critical Depth

--- 506_ras.f01 (steady flow) ---

Flow Title=Flow 01
Program Version=5.01
Number of Profiles= 5
Profile Names=10yr,25yr,50yr,100yr,500yr
River Rch & RM=506,24,2024.928
  632.39  811.48  983.58 1129.53 1456.09
River Rch & RM=506,24,1928.827
  634.03   813.9   986.6 1133.42 1461.83
River Rch & RM=506,24,1832.726
  639.72  822.28  997.06 1146.95  1481.8
River Rch & RM=506,24,1640.523
  648.52  835.26 1013.25 1167.94 1512.82
River Rch & RM=506,24,1544.422
  652.85  841.65 1021.23  1178.3 1528.18
River Rch & RM=506,24,1448.321
  656.36  846.84 1027.71 1186.72 1540.66
River Rch & RM=506,24,1352.219
  657.91  849.14 1030.58 1190.44 1546.19
River Rch & RM=506,24,1160.017
  659.46  851.42 1033.43 1194.15  1551.7
River Rch & RM=506,24,1063.916
  664.06  858.24 1041.95 1205.23 1568.16
River Rch & RM=506,24,967.8146
  668.24  864.43 1049.68  1215.3 1583.15
River Rch & RM=506,24,871.7134
  685.29  889.76 1081.34 1256.64 1644.84
River Rch & RM=506,24, 679.511
  688.19  894.07 1086.74  1263.7 1655.41
River Rch & RM=506,24,583.4098
  692.86  901.04 1095.45  1275.1 1672.49
River Rch & RM=506,24,416.4663
     695  904.23 1099.44 1280.33 1680.33
River Rch & RM=506,24,354.6052
  696.43  906.35 1102.09  1283.8 1685.55
River Rch & RM=506,24,199.0049
  701.02  913.19 1110.66 1295.04 1702.42
River Rch & RM=506,24,115.9504
  703.82  917.38  1115.9 1301.92 1712.75
River Rch & RM=506,24,  6.8025
  706.25  921.02 1120.46  1307.9 1721.76
Boundary for River Rch & Prof#=506,24,1
Up Type= 0
Dn Type= 2
Boundary for River Rch & Prof#=506,24,2
Up Type= 0
Dn Type= 2
Boundary for River Rch & Prof#=506,24,2
Up Type= 0
Dn Type= 2
Boundary for River Rch & Prof#=506,24,2
Up Type= 0
Dn Type= 2
Boundary for River Rch & Prof#=506,24,2
Up Type= 0
Dn Type= 2

--- 506_ras.g01 (geometry) ---

Geom Title=506
Program Version=4.10

River Reach=506,24
Reach XY= 30
1207146.70218839631438.6999104811207135.03552683 631497.03322682
1207091.70220783631550.3665455811206985.86890785631623.699860211
1206956.70225296631735.3664945851206991.70224496631816.199802887
1206973.36892027631927.8664369461207007.53557873631992.866416676
1207002.53558363632108.6997157641207037.53557477632160.366366073
1207030.86891183632220.3663484851207010.86891923632272.866333451
1207020.03558437632312.866321323  1207015.035588632390.366298483
1207033.36891655632411.1996251161207040.03558231632446.199614518
1207015.03559127632503.6995981781207015.86892656632578.699575898
1206969.20227491632620.3662315621206952.53561422632659.532887052
1206952.53561564632708.6995391481206965.03561277632736.199530613
1206958.36894958632786.1995159641206984.20227585632807.866175434
1207037.53559403632826.199501828  1207080.035584632914.532807696
1207085.86891767632986.1994529261207078.36892098633023.699442009
1207030.86893623633064.532764604   1207009.20228633206.199389836

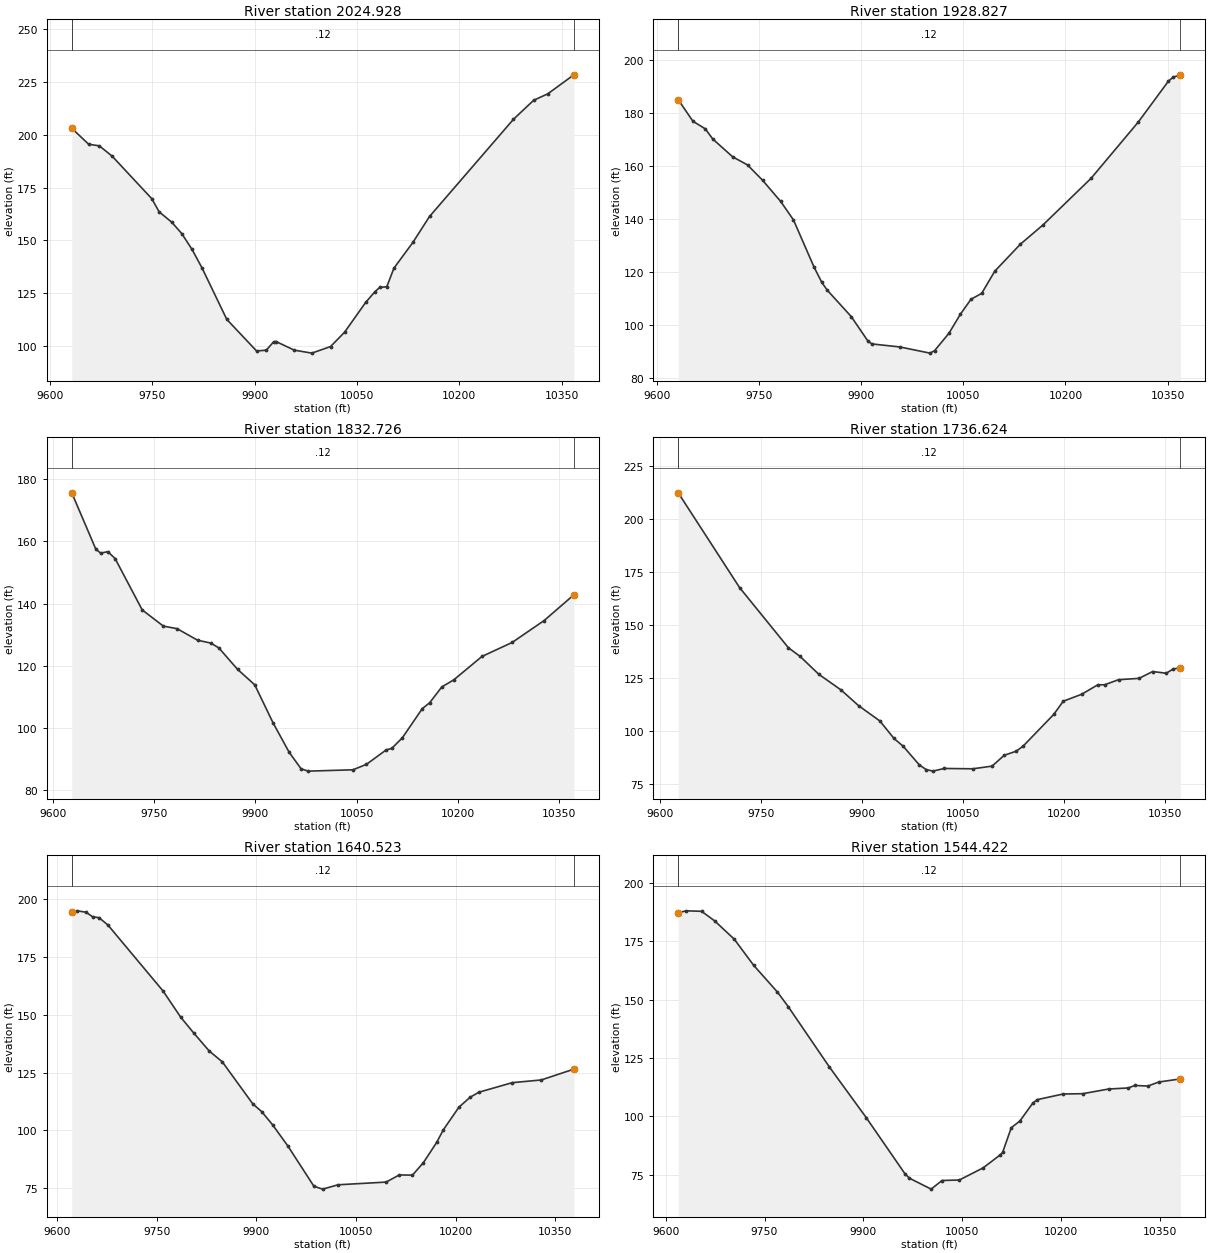
Type RM Length L Ch R = 1 ,2024.928,96.101200,96.101200,96.101200
XS GIS Cut Line= 6
1206811.76432365631288.1417428541207037.75622934 631397.68920723
1207089.23130238631420.4394044151207222.39441236631462.377714064
1207401.20211759631525.0625385821207495.59951818631554.891207336
#Sta/Elev= 30
9632.227203.12179657.026195.54319672.611194.79159691.252189.95899749.308169.8217
 9760.31163.53519778.646158.64839793.315153.28319808.436145.73669823.123136.9361
9859.324112.61969902.894  97.6799917.24298.003089928.003 102.022 9931.59102.1008
 9958.2898.035849983.91396.6323910011.3799.7454210031.91106.548810062.73120.6173
10076.43 125.73610083.34127.739110093.77128.0828 10104.2136.863510132.01149.0809
10156.35161.338410279.34207.3865 10308.9216.373210329.54219.420110367.79228.4278
#Mann= 3 , 0 , 0
9632.227    0.12       09632.227    0.12       010367.79    0.12       0
#XS Ineff= 2 , 0
       0                               0
Bank Sta=9632.227,10367.79
Exp/Cntr=0.3,0.1

Type RM Length L Ch R = 1 ,1928.827,96.101200,96.101200,96.101200
XS GIS Cut Line= 6
1206796.75708995631336.9039539271206990.38743439631438.970820372
1207155.01075178631559.8340037051207217.18651355631597.759191803
  1207306.199696   631637.7126061207443.11952093631681.128641309
#Sta/Elev= 30
9631.219185.01969652.728 176.8749670.978173.98589681.929 170.155 9711.13163.4261
9733.031160.34249755.025154.58179781.551146.61359800.497139.59669830.812 121.702
 9842.18115.95629850.237 113.0019885.387103.05679910.01593.75831 9915.8792.71533
9956.83591.57801   1000189.2458310007.7290.1584610028.8796.71623 10045.7103.9354
10061.31109.604110077.01111.8239 10096.3120.2246 10133.9130.411510166.82137.6205
10237.67155.285210306.94176.508310351.33192.000710358.16193.485810368.82194.3985
#Mann= 3 , 0 , 0
9631.219    0.12       09631.219    0.12       010368.82    0.12       0
#XS Ineff= 2 , 0
       0                               0
Bank Sta=9631.219,10368.82
Exp/Cntr=0.3,0.1

Type RM Length L Ch R = 1 ,1832.726,96.101200,96.101200,96.101200
XS GIS Cut Line= 6
1206740.87413865631378.5385139951206959.28893551631495.894341742
1207071.82333881631633.221513488 1207119.9542677631671.493069679
1207219.48758845 631715.925399721207360.79984832 631755.17097231
#Sta/Elev= 30
9627.545175.64659663.179 157.526 9670.36156.2313 9681.13156.6986  9691.9154.4535
9732.066137.93239763.426132.72769783.796131.89899814.235128.17779833.676127.2681
 9845.62125.72999873.488118.80069899.036113.80679926.105 101.5919950.078 92.0836
9967.83986.754469978.19186.0205410044.6786.4458710064.69 88.200410094.2392.88945
10102.1893.3197510117.9596.7477110147.44106.116210158.49108.046510176.61113.1546
 10194.2115.404510236.14122.958810280.75127.445710328.33 134.517 10372.4142.7962
#Mann= 3 , 0 , 0
9627.545    0.12       09627.545    0.12       0 10372.4    0.12       0
#XS Ineff= 2 , 0
       0                               0
Bank Sta=9627.545,10372.4
Exp/Cntr=0.3,0.1

Type RM Length L Ch R = 1 ,1736.624,96.101200,96.101200,96.101200
XS GIS Cut Line= 6
1206624.29816409631538.0516927171206773.36110348631585.033521711
1206939.58347109631643.9911119851207008.74685689631661.073561263
1207167.15132357631724.7445025241207331.68949017631768.240774935
#Sta/Elev= 30
  9627.5  212.499718.514167.68679790.836139.26729808.242 135.1549836.091126.6773
9869.076119.26259895.269111.79039926.599104.62679947.59196.356339961.37492.61323
9985.04583.87608 9995.1981.63962 10005.380.88117 10022.2 82.1412 10064.681.98577
10093.2283.25439 10111.188.3567410128.9790.3025610139.4392.7683510184.77107.7376
10198.72113.937410226.12 117.23110250.04121.702310260.29121.725410280.79124.1211
10311.21124.750610331.45127.979610351.69127.180310361.81 129.18210372.46129.7577
#Mann= 3 , 0 , 0
  9627.5    0.12       0  9627.5    0.12       010372.46    0.12       0
#XS Ineff= 2 , 0
       0                               0
Bank Sta=9627.5,10372.46
Exp/Cntr=0.3,0.1

Type RM Length L Ch R = 1 ,1640.523,96.101200,96.101200,96.101200
XS GIS Cut Line= 6
1206581.81632719631713.6077149511206741.21999345631738.542375758
1206854.55181453631749.8286291211207023.09662023631739.093615299
1207072.36807455631740.2175481061207330.15016089631790.333992571
#Sta/Elev= 30
9621.808194.17149629.799194.83589643.082194.25369653.044192.31199663.007191.8497
9676.289188.70229759.308160.23669785.859148.94389805.676142.03959828.796134.3429
9848.613129.63289894.684111.43169907.814108.18519924.218102.49339947.18493.37376
9986.66675.89345 9999.8574.6885410022.9576.5637910095.4177.72896 10115.180.81087
10135.0280.7283910151.6286.1615810171.55 94.875710181.51100.289310204.96110.0299
10221.71114.315910235.11 116.52510285.37 120.65110328.93121.811510378.14 126.486
#Mann= 3 , 0 , 0
9621.808    0.12       09621.808    0.12       010378.14    0.12       0
#XS Ineff= 2 , 0
       0                               0
Bank Sta=9621.808,10378.14
Exp/Cntr=0.3,0.1

Type RM Length L Ch R = 1 ,1544.422,96.101200,96.101200,96.101200
XS GIS Cut Line= 6
 1206610.1082544631819.9117354741206765.27325302631831.538431547
 1206952.8737486631829.7305558641207035.38157843631837.768276365
1207175.71100576631840.3729513181207370.30147511631858.922387138
#Sta/Elev= 30
9618.993187.28689631.454188.04819654.509187.83959674.271183.74289703.914175.9394
9733.506164.71189769.649153.23489786.062146.96699848.406121.1842  9904.299.54801
9963.28175.385749969.87573.5564310002.8468.8773610019.3272.5689510045.6972.79352
10081.7877.9828710108.0383.6181410111.3284.6181410124.4495.1593310137.5798.06004
10157.26105.769810163.82107.192710203.24109.617810232.85109.742810272.34  111.75
10302.05112.201510311.95113.270710331.76113.018510348.26114.738110381.02116.0677
#Mann= 3 , 0 , 0
9618.993    0.12       09618.993    0.12       010381.02    0.12       0
#XS Ineff= 2 , 0
       0                               0
Bank Sta=9618.993,10381.02
Exp/Cntr=0.3,0.1

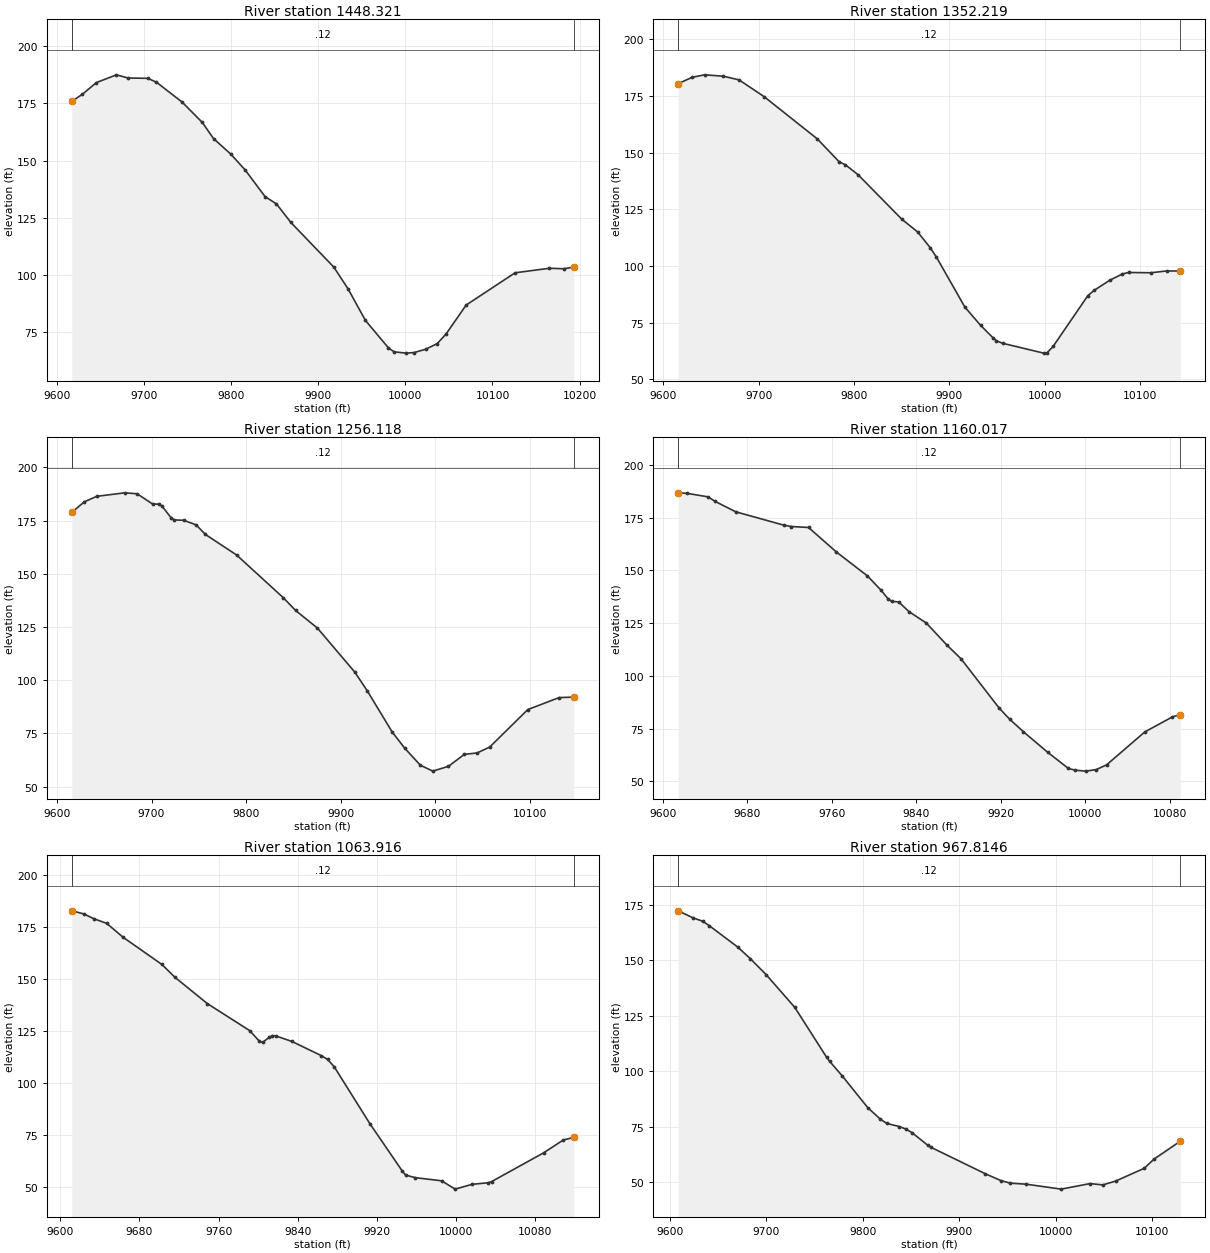
Type RM Length L Ch R = 1 ,1448.321,96.101300,96.101300,96.101300
XS GIS Cut Line= 6
  1206590.873793631938.034532105   1206713.77479631942.407927941
1206824.36356531631940.0202418961206986.15027747631926.175083273
1207084.74509434631911.4835483391207165.58229045631905.971271345
#Sta/Elev= 30
9616.701 175.941 9628.67178.95369645.085184.15919668.065187.52289681.197186.1435
9704.177185.98449714.026 184.284 9743.57175.56789766.542166.74419779.668159.6108
9799.358152.87949815.766145.98539838.737134.30999851.867131.09789868.315123.0215
9917.693103.49619934.19393.907729953.99380.195589980.39468.207529986.98666.43422
   1000165.8722510009.9966.1283710023.2667.5709610036.5770.0480910046.5574.16626
10069.8386.9131410125.97100.987510165.43102.969810181.88102.745110193.47103.4862
#Mann= 3 , 0 , 0
9616.701    0.12       09616.701    0.12       010193.47    0.12       0
#XS Ineff= 2 , 0
       0                               0
Bank Sta=9616.701,10193.47
Exp/Cntr=0.3,0.1

Type RM Length L Ch R = 1 ,1352.219,96.101200,96.101200,96.101200
XS GIS Cut Line= 6
1206627.63453973632037.674980433 1206737.8031688 632038.05039526
1206845.29391534632032.6758641391206901.75244042632026.963691393
1207011.59238614632012.6591874681207152.00571287631995.982644073
#Sta/Elev= 30
9615.691180.39669630.262183.17649643.385184.2776 9663.07183.66479679.475182.0591
9705.721174.6706 9761.54156.02479784.535145.89179791.105144.57599804.244140.2447
9850.298120.55149866.786114.98079879.976 108.0549886.571103.83979916.334 81.8416
9932.87673.75824 9946.1168.163639949.41866.975759956.03565.833439999.04361.49075
10002.3661.5416710008.9764.4389910045.3386.8089710051.94  89.17610068.4793.65185
10081.69 96.4511 10088.397.0672310111.4496.9515410127.9797.7402510142.41 97.7314
#Mann= 3 , 0 , 0
9615.691    0.12       09615.691    0.12       010142.41    0.12       0
#XS Ineff= 2 , 0
       0                               0
Bank Sta=9615.691,10142.41
Exp/Cntr=0.3,0.1

Type RM Length L Ch R = 1 ,1256.118,96.101200,96.101200,96.101200
XS GIS Cut Line= 6
1206619.03178378632125.6635399661206743.41382626632126.428001386
1206879.60204651632120.9332264821207010.79741409 632107.58115952
1207087.44854296632090.9813776921207146.57158717 632083.38149892
#Sta/Elev= 30
9615.701178.83189629.032183.80419642.156186.38749671.684188.02629684.807187.5798
9701.212182.74229707.774182.70339711.055181.82559720.897176.14769724.178175.2896
9734.021175.1167 9747.15172.95989757.001168.44899789.836158.82879839.088138.8037
9852.222132.76399875.207124.51619914.783103.78859927.97694.990159954.36475.60435
9967.55868.03359 9984.0560.028649997.24457.2317510013.8459.4970910030.6265.12422
10044.0565.7629110057.4868.57265 10097.686.1495410130.68 91.786310146.3392.02476
#Mann= 3 , 0 , 0
9615.701    0.12       09615.701    0.12       010146.33    0.12       0
#XS Ineff= 2 , 0
       0                               0
Bank Sta=9615.701,10146.33
Exp/Cntr=0.3,0.1

Type RM Length L Ch R = 1 ,1160.017,96.101200,96.101200,96.101200
XS GIS Cut Line= 6
1206646.76818113632192.1999982281206797.11647503632193.165067186
1206990.84428349632188.8284556511207031.01085751632190.535323475
1207032.99251786632190.805549821 1207122.0542147 632194.17889028
#Sta/Elev= 30
9614.669186.7604 9623.23 186.5019642.915184.85299649.477182.73269669.163177.7564
9715.095171.37629721.657170.79599738.062170.33089764.309158.76759793.844147.3641
 9806.97140.46119813.533136.41889816.815135.32219823.378135.04529833.223 130.439
9849.632125.01839869.322114.46649882.448108.10039918.54684.740789928.39179.51767
9941.51873.511269964.49363.786139984.19656.084389990.76455.2613710000.6354.83191
10010.4855.5506110020.3357.8054210056.4573.4015510082.7280.5556610090.1381.65103
#Mann= 3 , 0 , 0
9614.669    0.12       09614.669    0.12       010090.13    0.12       0
#XS Ineff= 2 , 0
       0                               0
Bank Sta=9614.669,10090.13
Exp/Cntr=0.3,0.1

Type RM Length L Ch R = 1 ,1063.916,96.101200,96.101200,96.101200
XS GIS Cut Line= 6
1206626.65802369632280.2791447341206960.09036432632288.051662577
1206994.88984156632285.8125236311207026.01463789632276.232985353
 1207044.5891147632274.2711455351207131.98003857632276.988620753
#Sta/Elev= 30
9611.739182.84849624.012181.35959633.859179.06629646.989176.82299663.401170.1773
 9702.79157.0281 9715.92150.86579748.744138.16689791.405125.19549801.249 120.058
 9804.53119.48669811.093121.96249814.374 122.7559817.655122.66499834.062119.9652
9863.594113.18689870.156111.30479876.719107.83819912.81380.393479945.62757.53958
9948.91555.633819958.77754.393049985.26552.886819998.91148.8774510016.0751.19046
10032.5651.9559910035.8452.5329910088.3666.3560910108.06 72.505110118.83 73.8116
#Mann= 3 , 0 , 0
9611.739    0.12       09611.739    0.12       010118.83    0.12       0
#XS Ineff= 2 , 0
       0                               0
Bank Sta=9611.739,10118.83
Exp/Cntr=0.3,0.1

Type RM Length L Ch R = 1 ,967.8146,96.101200,96.101200,96.101200
XS GIS Cut Line= 6
1206623.38382901 632365.866089771206844.51286256632377.347483358
1206926.24813426632379.1455432881207020.99702176632374.198907894
1207083.36739211632365.064096813 1207142.0220315632360.767533184
#Sta/Elev= 30
9608.962172.32849624.524169.11719634.379167.6253 9640.95165.67579670.517156.0038
9683.658150.72139700.084143.49229729.652128.76179762.504106.32069765.789104.4093
 9778.9397.760949805.212 83.51939818.35378.275799824.92476.399449838.056 74.9561
 9844.6273.868329851.18372.189799867.59166.466439870.87365.576019926.67553.73331
  9943.150.596289952.95549.42667 9969.3848.9674210005.5246.7419210035.3549.23871
10048.6248.6556310061.8850.3783510091.56 56.144210101.4360.2175110128.8868.36614
#Mann= 3 , 0 , 0
9608.962    0.12       09608.962    0.12       010128.88    0.12       0
#XS Ineff= 2 , 0
       0                               0
Bank Sta=9608.962,10128.88
Exp/Cntr=0.3,0.1

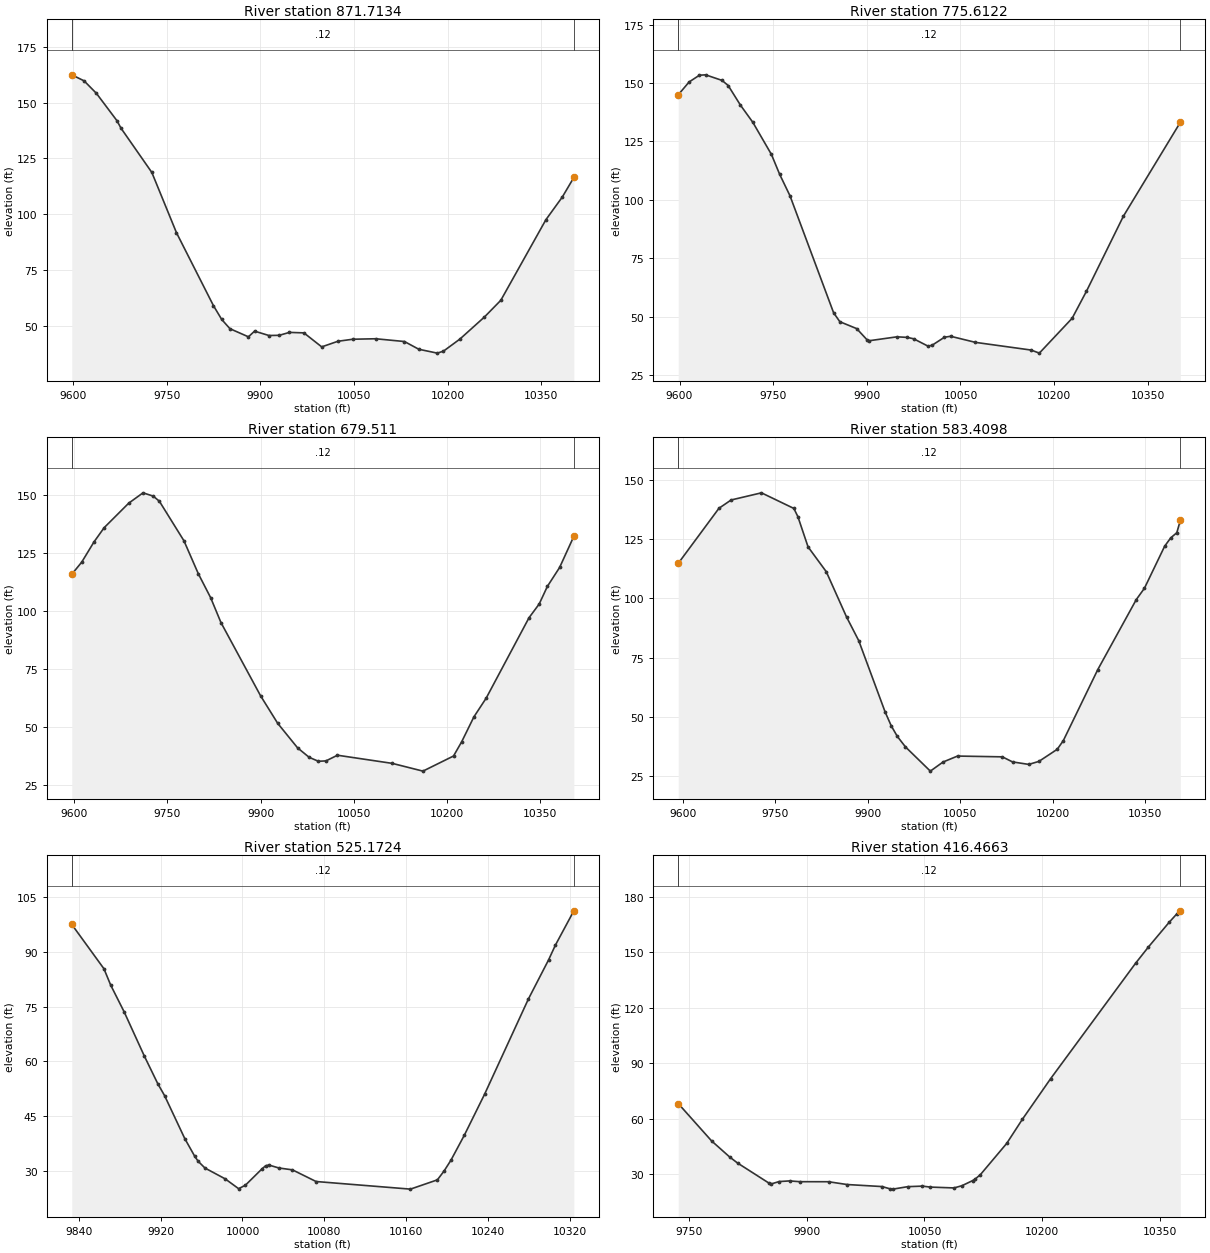
Type RM Length L Ch R = 1 ,871.7134,96.101200,96.101200,96.101200
XS GIS Cut Line= 6
1206632.37586411632420.2490939211206999.10158699632446.279637634
1207018.94460195632451.4710080911207058.52656573632472.303096718
1207125.01123286632482.9982234671207428.45073262632492.532287708
#Sta/Elev= 30
9597.939162.50139617.653159.80429637.381154.2042 9670.26141.93729676.835138.5393
9726.178118.70199765.67891.636989824.92758.899629838.09452.74129 9851.2648.59494
9880.86944.949149890.72847.493289913.73445.540879930.16745.62388  9946.646.93787
9969.73446.721129998.25440.4347910024.3342.9618710048.19 43.8698 10084.744.07994
10130.7842.8414610153.7839.3683310183.3537.6327810193.2138.5105710219.4943.91522
10258.8753.8337310285.1261.3393910357.3197.4858110383.56107.651210402.09116.4418
#Mann= 3 , 0 , 0
9597.939    0.12       09597.939    0.12       010402.09    0.12       0
#XS Ineff= 2 , 0
       0                10070.03       0
Bank Sta=9597.939,10402.09
Exp/Cntr=0.3,0.1

Type RM Length L Ch R = 1 ,775.6122,96.101200,96.101200,96.101200
XS GIS Cut Line= 6
1206621.50619234632492.6198937771206829.27480599632512.834773658
1206998.23777264632551.2692947981207049.37616266632552.325134242
1207203.08557382632570.1442149851207419.10556302632573.623475497
#Sta/Elev= 30
9597.909144.92399615.376150.42819631.827153.29569641.697153.46889668.018151.0879
9677.888148.90049697.629140.46819717.397 133.147 9747.15119.42219760.374110.8926
9776.903101.71229846.75251.668369856.77647.825859883.71444.880519900.69639.98578
9904.09339.703969948.24641.362649965.03841.118269975.04740.514399998.10137.36583
10004.6737.7802110024.3641.1929510034.2341.5960210073.9638.9920210163.1635.69841
10176.3334.3862710228.8749.3043910251.8560.8995810310.9292.9625710402.12 133.124
#Mann= 3 , 0 , 0
9597.909    0.12       09597.909    0.12       010402.12    0.12       0
#XS Ineff= 2 , 0
       0                10037.99       0
Bank Sta=9597.909,10402.12
Exp/Cntr=0.3,0.1

Type RM Length L Ch R = 1 , 679.511,96.101200,96.101200,96.101200
XS GIS Cut Line= 6
1206573.68160701632552.651578222 1206739.3029747632563.436831724
1206861.20004497632582.3060486751207013.90375412632653.715473757
1207062.53862532632667.4969366061207360.64016563632663.636079802
#Sta/Elev= 30
9596.004115.69349612.057120.9378 9631.77129.62449648.198135.76659687.625146.2831
9710.662150.74099727.118149.31799736.992147.11449776.553130.10019799.699115.9139
9819.539105.6098 9836.0994.931129899.90563.39873  9927.451.584699959.39341.03462
9978.00536.964719992.89535.2580310005.1135.4206710023.5737.8610810111.78 34.3539
10161.1331.0193110210.3737.52417 10223.543.65642 10243.254.3776410262.8962.41233
10331.8397.0007210348.25102.928710361.38110.480510381.08118.626910403.99132.0402
#Mann= 3 , 0 , 0
9596.004    0.12       09596.004    0.12       010403.99    0.12       0
#XS Ineff= 2 , 0
       0                10059.72       0
Bank Sta=9596.004,10403.99
Exp/Cntr=0.3,0.1

Type RM Length L Ch R = 1 ,583.4098,58.237400,58.237400,58.237400
XS GIS Cut Line= 6
1206549.93941506632744.0917799321206870.36154326632731.023209376
1206930.38434742632724.6246945041207026.41408639632702.729290638
1207215.87869392632685.9131447611207359.81000972632678.917517259
#Sta/Elev= 30
9592.936 114.7769658.971138.00959678.661141.50439727.885144.52549780.436137.9435
9787.009134.43689803.441121.7318 9833.02111.24659865.88692.155159885.60582.19826
9928.38852.125829938.286  46.2919948.18541.806959961.38237.3854310001.7327.16564
10022.3231.0053210045.8533.5220110118.5133.1896910134.9831.0523410161.3330.00037
 10177.831.2742810207.4436.3653810217.3240.0087610273.2970.01057 10335.799.52263
10348.84 104.26510381.68122.014510391.54125.538910401.39127.699110407.06 132.877
#Mann= 3 , 0 , 0
9592.936    0.12       09592.936    0.12       010407.06    0.12       0
#XS Ineff= 2 , 0
       0                10057.88       0
Bank Sta=9592.936,10407.06
Exp/Cntr=0.3,0.1

Type RM Length L Ch R = 1 ,525.1724,108.706100,108.706100,108.706100
XS GIS Cut Line= 3
1206791.27225292632763.0780549791207000.67733568632774.976071045
1207280.28071329632753.559642121
#Sta/Elev= 30
9833.343 97.52259864.77285.362479871.34580.888999884.48973.552019904.20661.43415
 9917.3553.844589923.92350.616019943.63938.837469953.49833.916619956.784 32.5903
9963.35630.754619983.07327.789499996.21725.0945910002.7926.0258110019.22 30.5655
10022.5131.3474810025.7931.5689810035.6530.75702 10048.830.2524710071.8427.05497
10163.9724.9683810190.2927.5125110196.8729.9587410203.45 32.861810216.6239.75789
10236.3650.9743810279.1377.0767310298.8887.8213910305.4691.8257110323.51  101.25
#Mann= 3 , 0 , 0
9833.343    0.12       09833.343    0.12       010323.51    0.12       0
#XS Ineff= 2 , 0
       0                10040.93       0
Bank Sta=9833.343,10323.51
Exp/Cntr=0.3,0.1

Type RM Length L Ch R = 1 ,416.4663,61.861100,61.861100,61.861100
XS GIS Cut Line= 5
1206780.56403846632820.188532114 1206982.8303116 632847.55396907
1207076.82463855632817.8089288921207193.42519599632792.823095158
1207411.15889007 632795.20269835
#Sta/Elev= 30
 9736.2868.15008 9778.7547.921529801.92539.160729811.858 35.93259851.58625.13217
9854.89724.630279864.82925.893329878.07226.247159891.31525.823699927.73325.80588
9951.32324.290789996.05823.1818810006.3821.9222610009.8221.7963810028.7723.13556
10047.4623.4241310057.5222.8995910087.72 22.442510097.7923.6548410111.2126.37967
10114.57  27.24610121.2829.6499810154.8346.5796110174.5959.5268610210.6881.58184
10318.96144.122810335.36152.954610361.61166.239410371.45170.846410375.97172.5291
#Mann= 3 , 0 , 0
 9736.28    0.12       0 9736.28    0.12       010375.97    0.12       0
#XS Ineff= 2 , 0
       09926.538                       0
Bank Sta=9736.28,10375.97
Exp/Cntr=0.3,0.1

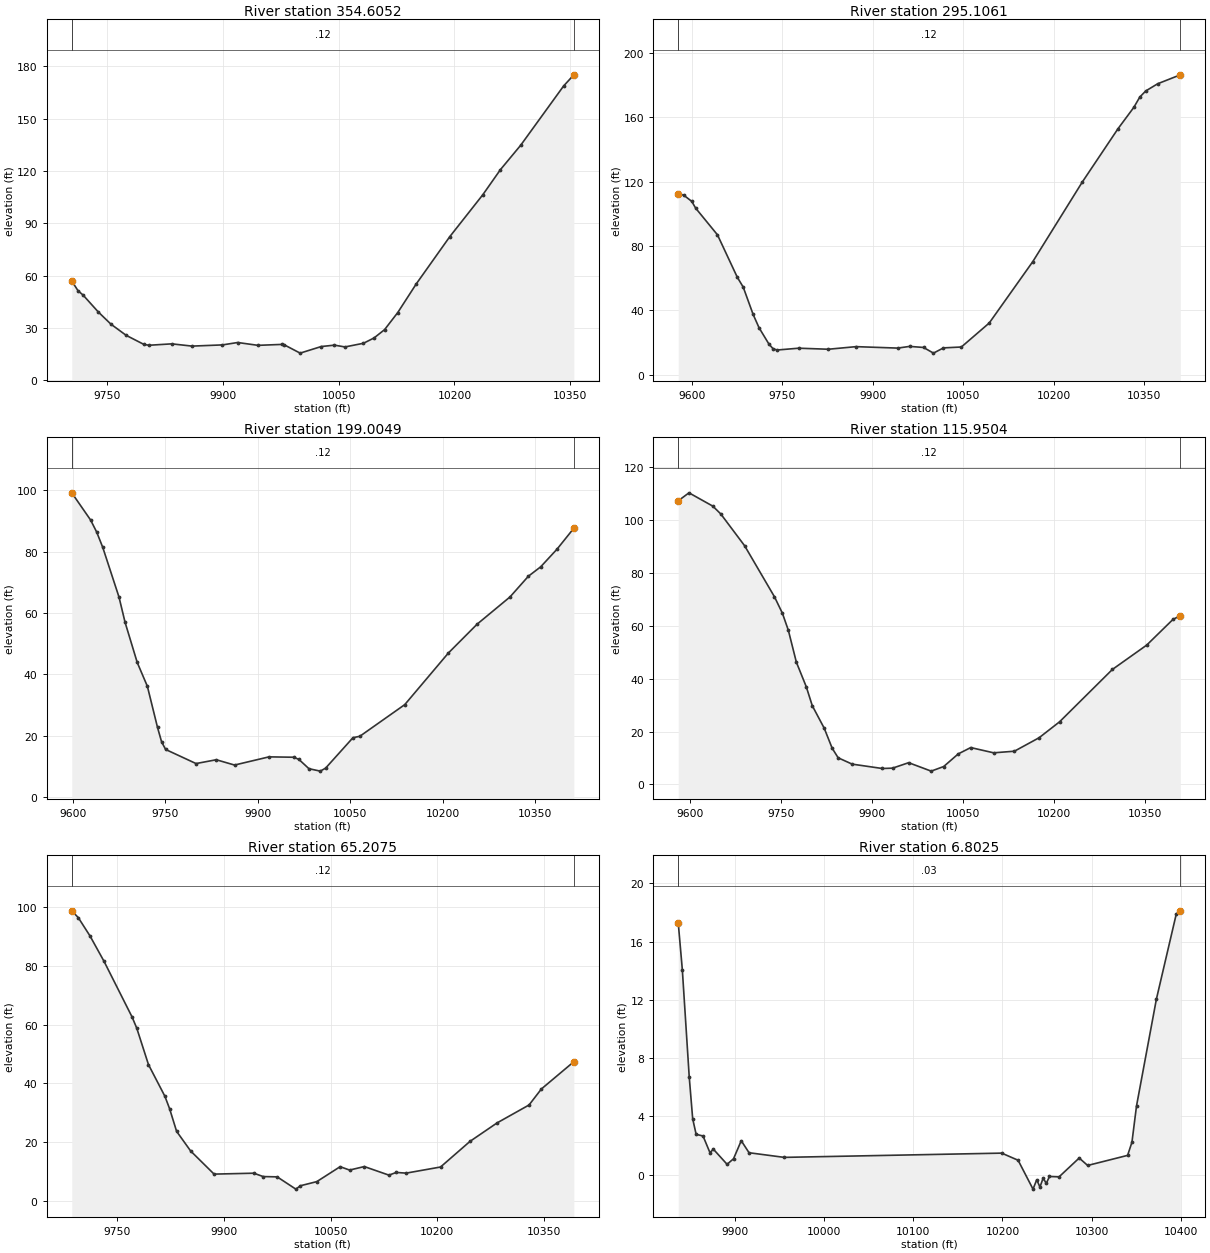
Type RM Length L Ch R = 1 ,354.6052,59.499100,59.499100,59.499100
XS GIS Cut Line= 4
1206768.66602239 632884.437818871207011.38555017632899.905239761
1207227.92944258 632835.655952991207409.96908844 632835.65595299
#Sta/Elev= 30
9703.78857.062459711.85751.470499718.43248.973369738.15739.290599754.59532.28392
 9774.3225.888059797.332  20.6839803.90720.197899833.495 21.00259859.79419.70969
9899.24420.402569918.96921.774959945.26920.145929975.998 20.6794 9979.4220.42683
9999.95315.6869410027.3319.4687710044.4420.2578710058.1319.2354110082.0921.33756
10095.7724.3781410109.4529.1436210126.5738.9587210150.5355.36185 10194.182.48904
10236.75106.409110259.72120.867510285.97134.834510341.74168.872310354.91 175.201
#Mann= 3 , 0 , 0
9703.788    0.12       09703.788    0.12       010354.91    0.12       0
#XS Ineff= 2 , 0
       09935.168                       0
Bank Sta=9703.788,10354.91
Exp/Cntr=0.3,0.1

Type RM Length L Ch R = 1 ,295.1061,96.101200,96.101200,96.101200
XS GIS Cut Line= 6
1206659.20427456632951.0667088481206986.69276536632946.131673127
1207193.28141007632927.2001905441207257.91908497632924.147146523
1207392.15743697 632924.396191181207490.12026876632928.116607577
#Sta/Elev= 30
9577.398112.55789586.647111.54879599.772107.74819606.334 103.5019642.42786.94149
9675.23960.629119685.08354.474179701.48937.522179711.33329.226229727.739 19.0666
9734.30116.298729740.86415.387799776.95716.526699826.17515.882169872.11217.49307
9941.113 16.59319960.85317.645429983.88316.9874510000.3613.4656210016.9416.71989
10046.6117.2696210092.7632.1664410165.09 70.383410247.13119.833610306.19152.8786
10332.45166.1667 10342.3172.551710352.15176.332710371.85180.789810409.43186.3536
#Mann= 3 , 0 , 0
9577.398    0.12       09577.398    0.12       010409.43    0.12       0
#XS Ineff= 2 , 0
       09919.318                       0
Bank Sta=9577.398,10409.43
Exp/Cntr=0.3,0.1

Type RM Length L Ch R = 1 ,199.0049,83.054500,83.054500,83.054500
XS GIS Cut Line= 6
1206680.62070346633024.8344084921207040.13783607633003.277135581
1207099.81029835633054.3606616851207160.49119198633081.626245052
1207270.14825591633108.6361199171207463.17067584633138.525925413
#Sta/Elev= 30
9598.36199.189289628.89890.327979638.75886.399189648.61881.401479674.91265.23754
9684.77256.998839704.49343.905359720.92636.15048 9737.3622.754969743.93318.09441
9750.50715.570339799.80810.976749832.675 12.21669862.25510.48945 9918.1313.15709
9958.52413.034859966.71612.301959982.9189.29910710001.248.50947310009.919.488934
10054.2319.39658 10065.419.8674710138.2430.1805510208.9646.9999210255.6256.40961
10308.8665.26837 10338.772.0261310358.5875.0780810385.0880.8316210412.3587.66069
#Mann= 3 , 0 , 0
9598.361    0.12       09598.361    0.12       010412.35    0.12       0
#XS Ineff= 2 , 0
       0  9921.3                       0
Bank Sta=9598.361,10412.35
Exp/Cntr=0.3,0.1

Type RM Length L Ch R = 1 ,115.9504,50.742900,50.742900,50.742900
XS GIS Cut Line= 6
1206608.06046081633060.9810014711206816.86977433633061.137458984
1206934.09587285633071.3573089821207007.51998389633086.378411377
1207214.46811492633147.188166455 1207422.0107576633186.417826831
#Sta/Elev= 30
9580.344107.21969598.085110.23149637.455105.19099650.578102.23529689.94890.20677
9739.161 70.91619752.28464.691419762.12758.19692 9775.2546.222899791.65836.89341
9801.51729.762879821.235 21.2476 9834.3813.672959844.23910.064019867.3227.668776
9917.039 6.017629934.0146.1510049960.5738.2142699997.754 5.0239810018.366.759333
10042.3911.5327910062.9913.9311610100.7611.9473710135.0212.5498410175.7517.63484
10209.5523.65723 10296.743.4537910353.3152.6545610396.5762.3453410408.8363.80848
#Mann= 3 , 0 , 0
9580.344    0.12       09580.344    0.12       010408.83    0.12       0
#XS Ineff= 2 , 0
       09967.379                       0
Bank Sta=9580.344,10408.83
Exp/Cntr=0.3,0.1

Type RM Length L Ch R = 1 , 65.2075,58.405000,58.405000,58.405000
XS GIS Cut Line= 4
1206702.03713235633116.4491322191206942.37705696633139.055362731
1207088.72265461633142.6247675721207390.93226275633243.757904142
#Sta/Elev= 30
9685.91998.738659695.02596.447969711.50190.208679731.27381.550459770.81762.54453
9777.40858.723669793.88446.316399816.95135.549759823.54231.329919833.42823.59746
  9853.216.901739886.1539.0246269942.1129.336427 9955.248.1862649974.9318.089342
10001.193.90779110007.755.06532310030.726.46696510063.54 11.554210076.8310.40264
10097.58 11.595410132.188.67668510142.569.595368 10156.49.35632610204.8311.44653
10246.3520.1978410284.4126.4797510329.3832.5820710346.6838.0264510392.3947.32782
#Mann= 3 , 0 , 0
9685.919    0.12       09685.919    0.12       010392.39    0.12       0
#XS Ineff= 2 , 0
       09971.695        10050.09       0
Bank Sta=9685.919,10392.39
Exp/Cntr=0.3,0.1

Type RM Length L Ch R = 1 ,  6.8025,0.000000,0.000000,0.000000
XS GIS Cut Line= 6
1206858.14321619633230.2691537141206920.85408226633194.089807898
1206989.35364369633194.0898078981207067.98342192633210.491111338
1207279.75319272633293.9448022991207361.27731857633372.092189252
#Sta/Elev= 30
9836.95517.284799841.52514.078139849.2586.7091799853.125 3.836459856.9912.763949
9864.7252.6486899872.4581.5071279876.3241.7428269891.6610.7039079898.8821.086879
9907.5182.3233839916.2531.4999239955.623 1.18105 10199.21.47262410217.550.983327
10234.26  -0.99910238.44-0.35483   10242-0.8587110245.57-0.2483410249.14-0.59961
 10252.7 -0.131710263.41-0.1570210285.971.13630810295.430.62604810340.181.318072
10345.03 2.2199810350.154.71017210372.4312.0480310394.7217.89971 10399.218.10814
#Mann= 3 , 0 , 0
9836.955    0.03       09836.955    0.03       0 10399.2    0.03       0
#XS Ineff= 2 , 0
       09970.919        10038.85       0
Bank Sta=9836.955,10399.2
Exp/Cntr=0.3,0.1